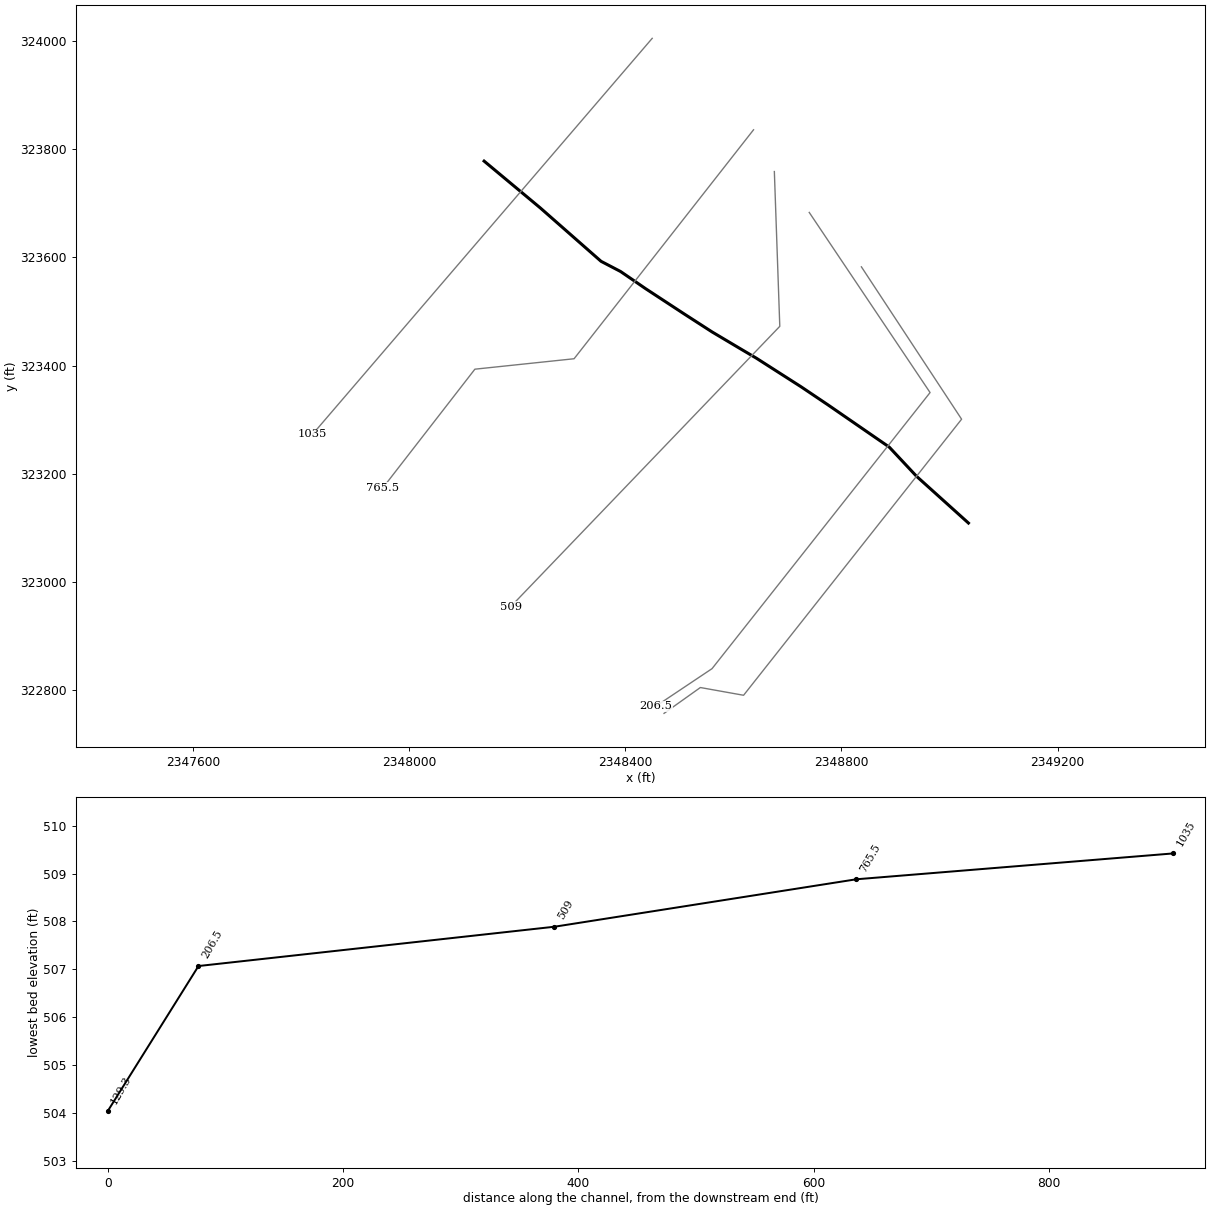
--- BACKTRIB1.prj (project) ---

Proj Title=BACKTRIB1
Current Plan=p01
Default Exp/Contr=0,0
English Units
Geom File=g01
Flow File=f01
Plan File=p01
BEGIN DESCRIPTION:
END DESCRIPTION:
DSS Export Rating Curves= 0
DSS Export Rating Curve Sorted= 0
DSS Export Volume Flow Curves= 0
DXF OffsetX= 0
DXF OffsetY= 0
DXF ScaleX= 0
DXF ScaleY= 0

--- BACKTRIB1.p01 (plan) ---

Plan Title=Floodplain
Program Version=4.00
Geom File=g01
Flow File=f01
K Sum by GR=0
Std Step Tol=0.01
Critical Tol=0.01
Num of Std Step Trials=20
Max Error Tol=0.3
Flow Tol Ratio=0.001
Split Flow NTrial=30
Split Flow Tol=0.02
Split Flow Ratio=0.02
Log Output Level=0
Friction Slope Method=1
Unsteady Friction Slope Method=2
Unsteady Bridges Friction Slope Method=1
Global Log Level=0
CheckData=False
Run HTab=0
Run UNet=0
Run PostProcess=0
UNET Theta=0
UNET Theta Warmup=0
UNET ZTol=0
UNET ZSATol=0
UNET MxIter=0
UNET MaxInSteps=0
UNET DtIC=0
UNET DtMin=0
UNET MaxCRTS=0
UNET WFStab=0
UNET SFStab=0
UNET WFX=0
UNET SFX=0
UNET DSS MLevel=0
UNET DZMax Abort=0
UNET Convert EG Bridges=0
UNET Use Existing IB Tables=0
UNET Froude Limit=0
UNET Froude Power=0
Write IC File=0
Echo Input=False
Echo Output=False
Write Detailed=0

--- BACKTRIB1.f01 (steady flow) ---

Flow Title=NFF Regression Equation
Program Version=4.00
Number of Profiles=1
Profile Names=P100yr
River Rch & RM=BACKTRIB1,Main      ,1035
571.8789
River Rch & RM=BACKTRIB1,Main      ,509
575.5201
River Rch & RM=BACKTRIB1,Main      ,206.5
576.1125
Boundary for River Rch & Prof#=BACKTRIB1,Main      ,1
Up Type=0
Dn Type=3
Dn Slope=0.014297

--- BACKTRIB1.g01 (geometry) ---

Geom Title=USGS 10m DEM
Program Version=4.10

River Reach=BACKTRIB1       ,Main
Reach XY= 17
     2348138.757      323778.388     2348242.923      323691.582
     2348355.175      323592.937      2348391.25      323574.101
     2348421.415      323553.485     2348437.148      323542.634
     2348509.523      323495.216     2348560.846      323462.122
     2348611.953       323431.74     2348642.661      323413.619
     2348725.451      323360.668     2348775.148      323327.248
     2348887.452      323249.882     2348887.754      323249.561
     2348888.756      323248.874     2348939.104      323195.054
     2349035.143      323108.548

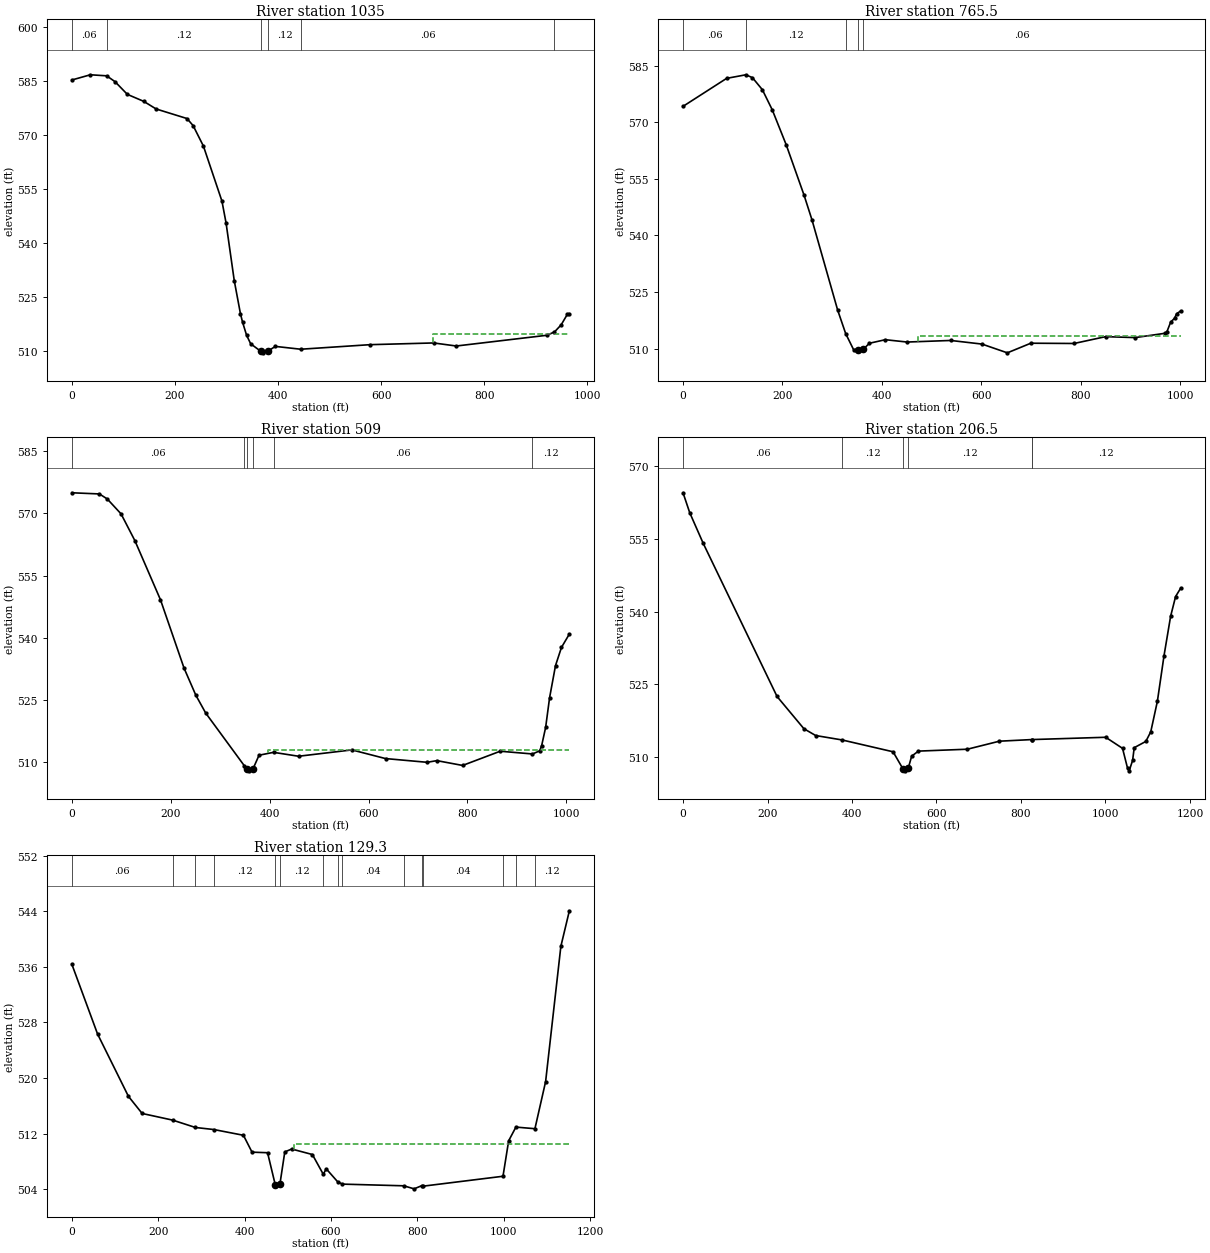
Type RM Length L Ch R = 1 ,1035    ,268.5,269.5,270.6
XS GIS Cut Line= 2
     2348449.882      324005.596      2347821.41      323272.957
#Sta/Elev= 30
       0   585.3    35.9  586.75   67.53586.4594    83.8  584.83   107.7   581.3
   139.6  579.35   163.5  577.24   223.4  574.58   235.3  572.61   255.3  566.91
   291.2  551.62   299.2  545.55   315.1   529.5   327.1  520.31   331.1  518.01
     339  514.32     347  511.93   366.3  509.88     371  509.42   381.3  509.99
   394.9  511.21  444.02510.4238   578.4  511.69     702  512.17   745.9  511.32
   921.4   514.3  936.45515.2332   949.3  517.19   961.3  520.11   965.3  520.28
#Mann= 6 ,-1 , 0
       0     .06       0   67.53     .12       0   366.3    .045       0
   381.3     .12       0  444.02     .06       0  936.45     .12       0
#XS Ineff= 2 , 0
                          700.72           514.7
Permanent Ineff=
       F       F
Bank Sta=366.3,381.3
XS Rating Curve= 0 ,0
Exp/Cntr=0.3,0.1

Type RM Length L Ch R = 1 ,765.5   ,258.4,256.5,253.8
XS GIS Cut Line= 4
     2348637.382      323836.325     2348305.284      323412.614
       2348121.7      323393.291     2347951.618      323173.999
#Sta/Elev= 30
       0  574.19    87.7  581.61  126.48582.5572   139.6  581.79   159.5  578.61
   179.4  573.28   207.4  564.04   243.2  550.73   259.2  544.17     311  520.19
  327.13513.9656     343  509.72   350.9  509.74   362.9  509.87   374.8  511.42
   406.8  512.36   450.6  511.74   538.4  512.16   601.2   511.2   652.2  508.88
   699.4  511.43   786.4  511.36   849.8  513.17   909.3  512.92   968.8  514.05
   972.7  514.33   980.6  517.01   988.6  518.06   992.5  519.22  1000.5  519.95
#Mann= 5 ,-1 , 0
       0     .06       0  126.48     .12       0  327.13     .06       0
   350.9    .045       0   362.9     .06       0
#XS Ineff= 2 , 0
                          471.83          513.38
Permanent Ineff=
       F       F
Bank Sta=350.9,362.9
XS Rating Curve= 0 ,0
Exp/Cntr=0.3,0.1

Type RM Length L Ch R = 1 ,509     ,300.5,302.5,305
XS GIS Cut Line= 3
     2348675.924      323759.068     2348685.993       323472.61
      2348187.73      322953.513
#Sta/Elev= 30
       0  574.97    55.7  574.69    71.7  573.47    99.5  569.88   127.4  563.44
   179.2  549.17   226.9  532.67   250.8  526.12   270.7  521.83  349.12509.0661
   354.6  508.35   358.6  507.89   366.6  508.43   378.6  511.66  407.93512.3534
   458.5  511.41   566.4  512.94   634.4  510.85   718.4  509.95   738.3  510.35
   790.3  509.19   866.3  512.62  931.56511.9614   946.2  512.71   950.2     514
   958.2  518.36   966.2  525.53   978.2  533.29   990.2  537.66  1006.2  540.89
#Mann= 6 ,-1 , 0
       0     .06       0  349.12     .12       0   354.6    .045       0
   366.6     .12       0  407.93     .06       0  931.56     .12       0
#XS Ineff= 2 , 0
                          397.52          512.97
Permanent Ineff=
       F       F
Bank Sta=354.6,366.6
XS Rating Curve= 0 ,0
Exp/Cntr=0.3,0.1

Type RM Length L Ch R = 1 ,206.5   ,77.1,77.2,77.1
XS GIS Cut Line= 4
     2348740.507      323683.374     2348964.118      323350.041
     2348560.646      322839.103      2348456.48      322769.485
#Sta/Elev= 30
       0  564.56    15.9  560.43    47.7  554.12   222.6  522.44   286.1  515.78
     314  514.37  376.65513.4531   497.2  511.01   520.2507.5363   525.2  507.07
   533.2  507.63   541.2   510.1   557.2  511.15     673  511.54   748.9   513.2
  825.32513.5327  825.65513.5343  1000.5  514.01  1040.4  511.72  1052.4  507.56
  1056.3  507.12  1064.2  509.22  1068.1  511.86  1095.5  513.15  1107.2  515.14
  1122.9  521.46  1138.6  530.88  1154.2  539.02    1166  543.11  1177.7  544.79
#Mann= 6 ,-1 , 0
       0     .06       0  376.65     .12       0   520.2    .045       0
   533.2     .12       0  825.32     .06       0  825.65     .12       0
Bank Sta=520.2,533.2
XS Rating Curve= 0 ,0
Exp/Cntr=0.3,0.1

Type RM Length L Ch R = 1 ,129.3   ,130.8,129.3,127.9
XS GIS Cut Line= 5
     2348837.035       323582.68     2349022.452      323300.735
      2348618.98      322789.798      2348538.98      322804.128
     2348471.757      322756.291
#Sta/Elev= 30
       0  536.37    59.6  526.32     131  517.36   162.8  514.89  233.75 513.928
  286.27512.8718  328.84512.5779   397.4  511.75   417.3  509.32   453.3  509.24
  471.04504.6426   481.8504.6785   493.2  509.36   509.2  509.77   557.1  508.98
  582.38  506.13   589.1  506.93  615.67505.0533  626.59  504.72   768.6 504.477
   792.8  504.04  810.94504.5109  812.23504.4149  998.57505.8509  1011.7  510.96
 1028.47512.9281 1072.53 512.697  1097.3  519.48  1132.6  538.95  1152.3  544.07
#Mann= 15 ,-1 , 0
       0     .06       0  233.75     .12       0  286.27    .016       0
  328.84     .12       0  471.04    .045       0   481.8     .12       0
  582.38     .04       0  615.67     .12       0  626.59     .04       0
   768.6    .016       0  810.94     .12       0  812.23     .04       0
  998.57     .12       0 1028.47    .016       0 1072.53     .12       0
#XS Ineff= 2 , 0
                          513.93          510.56
Permanent Ineff=
       F       F
Bank Sta=471.04,481.8
XS Rating Curve= 0 ,0
Exp/Cntr=0.3,0.1

Chan Stop Cuts=-1
Use User Specified Reach Order=0
Composite Channel Slope=5